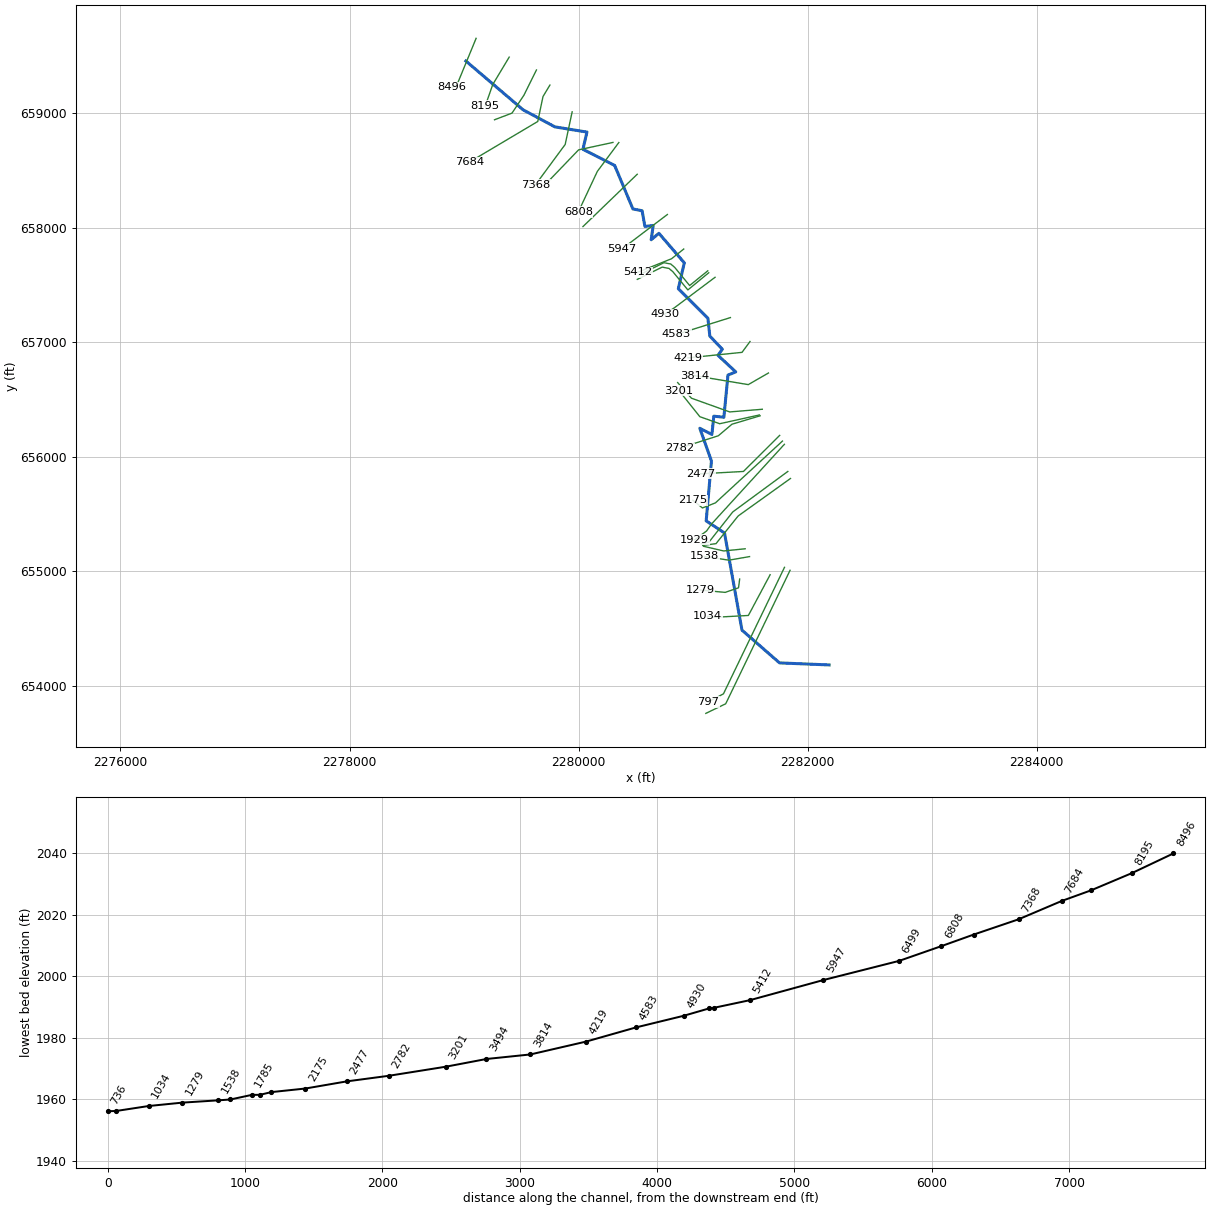
--- CSSTYRN.prj (project) ---

Proj Title=CSSTYRN
Current Plan=p01
Default Exp/Contr=0,0
English Units
Geom File=g01
Flow File=f01
Plan File=p01
BEGIN DESCRIPTION:
----------MODEL BY WOOD PLC 2022----------
AFH study
Randolph County, WV
HEC-RAS Version: RAS 6.2
Vertical Datum: NAVD88
Projection: NAD 1983 StatePlane West Virginia S FIPS 4702 (US Feet)
Terrain: 1-meter LIDAR (FEMA Region III 3DEP collected 2016-2018)
Land Use: 2019 NLCD
Hydrologic Method:
WV SIR2010-5033 regression equations
Additional Model Notes:
None
END DESCRIPTION:
DSS Export Rating Curves= 0
DSS Export Rating Curve Sorted= 0
DSS Export Volume Flow Curves= 0
DXF OffsetX= 0
DXF OffsetY= 0
DXF ScaleX= 0
DXF ScaleY= 0

--- CSSTYRN.p01 (plan) ---

Plan Title=Floodplain
Program Version=6.20
Short Identifier=Floodplain
Geom File=g01
Flow File=f01
Subcritical Flow
K Sum by GR= 0
Std Step Tol= 0.01
Critical Tol= 0.01
Num of Std Step Trials= 20
Max Error Tol= 0.3
Flow Tol Ratio= 0.001
Split Flow NTrial= 30
Split Flow Tol= 0.02
Split Flow Ratio= 0.02
Log Output Level= 0
Friction Slope Method= 1
Unsteady Friction Slope Method= 2
Unsteady Bridges Friction Slope Method= 1
Parabolic Critical Depth
Global Vel Dist= 0 , 0 , 0
Global Log Level= 0
CheckData=True
Encroach Param=-1 ,0,0, 0
Mapping Interval=1HOUR
Computation Time Step Use Courant=        0
Computation Time Step Use Time Series=    0
Computation Time Step Count To Double=0
Computation Time Step Max Doubling=0
Computation Time Step Max Halving=0
Computation Time Step Residence Courant=0
Run HTab= 0
Run UNet= 0
Run Sediment= 0
Run PostProcess= 0
Run WQNet= 0
Run RASMapper=-1
UNET Theta= 0
UNET Theta Warmup= 0
UNET ZTol= 0
UNET ZSATol= 0
UNET MxIter= 0
UNET Max Iter WO Improvement= 0
UNET MaxInSteps= 0
UNET DtIC= 0
UNET DtMin= 0
UNET MaxCRTS= 0
UNET WFStab= 0
UNET SFStab= 0
UNET WFX= 1
UNET SFX= 1
UNET Gravity=32.174
UNET 1D Methodology=Finite Difference
UNET DSS MLevel= 1
UNET Pardiso=0
UNET DZMax Abort= 0
UNET Use Existing IB Tables= 0
UNET Froude Reduction=False
UNET Froude Limit= 0
UNET Froude Power= 0
UNET D1 Cores= 0
UNET WindReference=Eulerian
UNET WindDragFormulation=Hsu (1988)
UNET D2 Coriolis=0
UNET D2 Cores= 0
UNET D2 Theta= 1
UNET D2 Theta Warmup= 1
UNET D2 Z Tol= 0.01
UNET D2 Volume Tol= 0.01
UNET D2 Max Iterations= 20
UNET D2 Equation= 0
UNET D2 RampUpFraction=0.1
UNET D2 TimeSlices= 1
UNET D2 Turbulence Formulation=Non-Conservative (original)
UNET D2 Eddy Viscosity=0.3
UNET D2 Transverse Eddy Viscosity=0.1
UNET D2 Smagorinsky Mixing=0
UNET D2 BCVolumeCheck=0
UNET D2 Cores=0
UNET D2 SolverType=PARDISO (Direct)
UNET D2 Minimum Iterations= 2147483647
UNET D2 Maximum Iterations= 2147483647
UNET D2 Restart Number= 10
UNET D2 Relaxation Coeff=1.3
UNET D2 SOR Precondition Iterations= 10
UNET D2 ILUT Maximum Fill= 8
UNET D2 ILUT Tolerance=1E-08
UNET D1D2 MaxIter= 0
UNET D1D2 ZTol=0.01
UNET D1D2 QTol=0.1
UNET D1D2 MinQTol=1
Write IC File= 0
Write IC File at Fixed DateTime=0
Write IC File at Sim End=0
Echo Input=False
Echo Parameters=False
Echo Output=False
Write Detailed= 0
HDF Write Warmup=0
HDF Write Time Slices=0
HDF Flush=0
HDF Compression= 1
HDF Chunk Size= 1
HDF Spatial Parts= 1
HDF Use Max Rows=0
HDF Fixed Rows= 1
Calibration Method= 0
Calibration Iterations= 20
Calibration Max Change=0.05
Calibration Tolerance=0.2
Calibration Maximum=1.5
Calibration Minimum=0.5
Calibration Optimization Method= 1
WQ AD Non Conservative
WQ ULTIMATE=-1
WQ Max Comp Step=1HOUR
WQ Output Interval=15MIN
WQ Output Selected Increments= 0
WQ Output face flow=0
WQ Output face velocity=0
WQ Output face area=0
WQ Output face dispersion=0
WQ Output cell volume=0
WQ Output cell surface area=0
WQ Output cell continuity=0
WQ Output cumulative cell continuity=0
WQ Output face conc=0
WQ Output face dconc_dx=0
WQ Output face courant=0
WQ Output face peclet=0
WQ Output face adv mass=0
WQ Output face disp mass=0
WQ Output cell mass=0
WQ Output cell source sink temp=0
WQ Output nsm pathways=0
WQ Output nsm derived pathways=0
WQ Create Restart=0
WQ Fixed Restart=0
WQ System Summary=0
WQ Write To DSS=0
Sorting and Armoring Iterations= 10
XS Update Threshold= 0.02
Bed Roughness Predictor= 0
Hydraulics Update Threshold= 0.02
Energy Slope Method= 1
Volume Change Method= 1
Sediment Retention Method= 0
Sediment TS Multiplier= 1
Warm Up Method= 0
XS Weighting Method= 0
Number of US Weighted Cross Sections= 1
Number of DS Weighted Cross Sections= 1
Upstream XS Weight=0
Main XS Weight=1
Downstream XS Weight=0
Number of DS XS's Weighted with US Boundary= 1
Upstream Boundary Weight= 1
Weight of XSs Associated with US Boundary= 0
Number of US XS's Weighted with DS Boundary= 1
Downstream Boundary Weight= 0.5
Weight of XSs Associated with DS Boundary= 0.5
Percentile Method= 0
Sediment Output Level= 3
Mass or Volume Output= 0
Output Increment Type= 1
Profile and TS Output Increment= 1
Transport Output Increment 1
XS Output Flag= 0
XS Output Increment= 10
Read HDF5 Sediment Hotstart= 0
Sediment Hotstart Type= 0
Write Gradation File= 0
Read Gradation Hotstart= 0
Write HDF5 File= 1
Write Binary Output= 1
Write DSS Sediment File= 0
DSS Sediment Output Type= 1
SV Curve= 0
Specific Gage Flag= 0
Subcell Erosion Methods= 0
Subcell Deposition Methods= 0
Advection Scheme= 1
Matrix Solver= 0
Implicit Weighting Factor= 1
Maximum Outer Loop Convergence Iterations= 5
Convergence Maximum Absolute= 0.001
Convergence RMSE= 0.0001
Grain Fractions Max Abs Error= 0.001
Max Subgrid Regions= 1
Max Subgrid Length Scale= 3.402823E+38
Initial Layer Thickness= 3.402823E+38
Min Layer Thickness= 3.402823E+38
Max Layer Thickness= 3.402823E+38
Number of Layers= 5

--- CSSTYRN.f01 (steady flow) ---

Flow Title=Flow
Program Version=6.20
Number of Profiles= 1
Profile Names=P100yr
River Rch & RM=CSSTYRN,Main,8496
     464
Boundary for River Rch & Prof#=CSSTYRN,Main            , 1
Up Type= 0
Dn Type= 3
Dn Slope=0.00449
DSS Import GetInterval= 0
DSS Import GetPeak= 0
DSS Import FillOption= 0

--- CSSTYRN.g01 (geometry) ---

Geom Title=Geometry
Program Version=6.20

River Reach=CSSTYRN         ,Main
Reach XY= 30
     2279015.927      659454.444     2279515.406      659028.402
2279793.59412422658879.306500702      2280072.91      658833.896
 2280038.0563887 658683.92503559     2280315.001      658542.464
     2280474.255      658162.482     2280554.463      658147.204
2280578.96102174658010.3134029232280651.66035892658018.643535309
     2280633.739      657893.952     2280701.212      657950.237
     2280922.958      657692.369     2280870.823      657466.119
     2281129.293      657207.891     2281145.666      657052.996
     2281254.729      656938.202 2281217.1146061656884.526417937
     2281372.127      656740.171     2281304.209      656712.486
     2281268.534      656343.947     2281180.593      656353.288
     2281163.837       656193.59     2281058.387      656247.725
     2281159.983      655962.186     2281113.998      655439.204
2281274.02755492655333.761616876     2281426.498      654485.428
     2281754.576      654199.266     2282187.518      654181.545

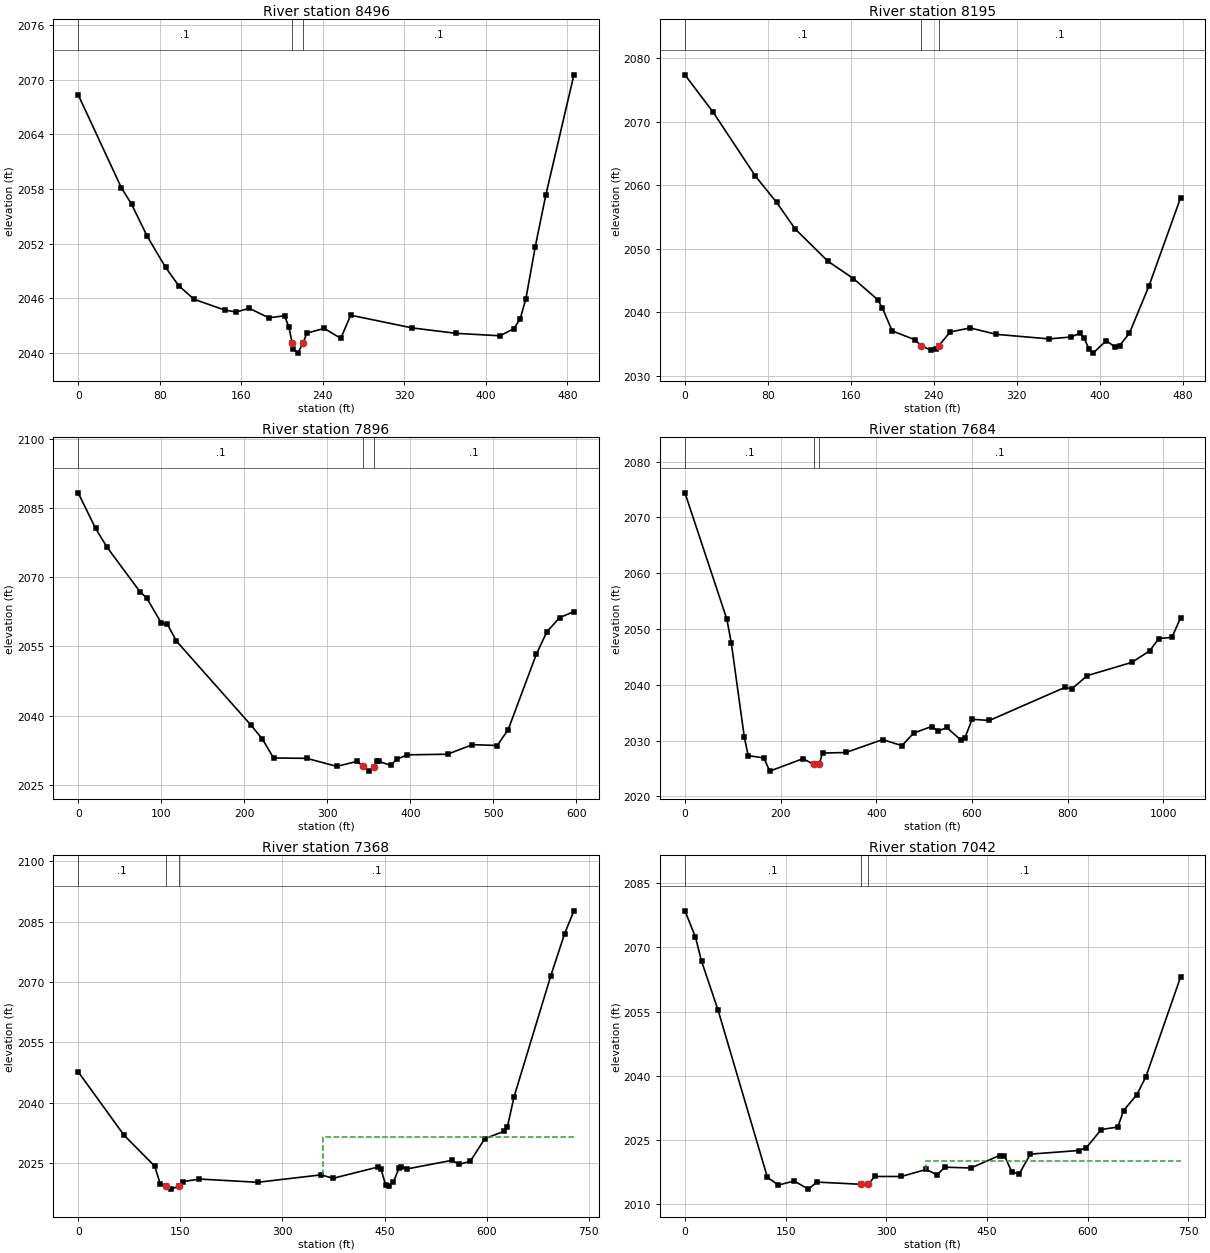
Type RM Length L Ch R = 1 ,8496    ,302.9,302,301.4
XS GIS Cut Line= 3
2279105.23218761659652.3852815812278939.51206522659249.836438109
2278895.39601049659224.331843963
#Sta/Elev= 30
       0 2068.33    42.4 2058.12    52.3 2056.34    67.6 2052.83    85.7  2049.4
    98.6 2047.39   113.6  2045.9   143.6 2044.72   154.9  2044.5   167.8 2044.91
   187.1 2043.86   202.4 2044.09   206.8 2042.83   209.8 2041.13   211.1 2040.42
   215.4 2039.99   220.8 2041.11   224.1 2042.18   241.4  2042.7   257.6 2041.61
   267.3 2044.15   327.9 2042.75     371 2042.16   413.9 2041.89   427.4 2042.68
   433.6 2043.75   439.2 2045.96   448.4 2051.67   458.7 2057.31   486.3 2070.52
#Mann= 3 ,-1,0
       0      .1       0   209.8    .045       0   220.8      .1       0
Bank Sta=209.8,220.8
XS Rating Curve= 0 ,0
Exp/Cntr(USF)=0,0
Exp/Cntr=0.3,0.1

Type RM Length L Ch R = 1 ,8195    ,297.2,298.6,295
XS GIS Cut Line= 3
2279394.20916963  659488.41061872279250.78934514659249.417508868
2279184.82151532659061.544128007
#Sta/Elev= 30
       0 2077.35    27.2 2071.47      68 2061.41    88.4 2057.28   106.4 2053.09
   137.9 2048.03   162.4 2045.31   185.7 2042.01   190.4 2040.67   199.7 2037.09
   221.6  2035.7   227.7 2034.75     237 2034.06   241.7 2034.17  244.59 2034.74
   255.7 2036.92     275 2037.55   300.2 2036.54     351 2035.83     372 2036.12
   380.7 2036.72     385 2035.92   389.2 2034.31   393.4 2033.59   406.2 2035.57
   414.6 2034.51   418.9 2034.77   428.4 2036.71   447.3 2044.16   477.8 2058.04
#Mann= 3 ,-1,0
       0      .1       0   227.7    .045       0  244.59      .1       0
Bank Sta=227.7,244.59
XS Rating Curve= 0 ,0
Exp/Cntr(USF)=0,0
Exp/Cntr=0.3,0.1

Type RM Length L Ch R = 1 ,7896    ,209.3,212,214.1
XS GIS Cut Line= 4
2279631.87290588659375.8664978422279522.47670993659155.490528698
2279418.63755562658999.3874964362279265.89978868658941.302825653
#Sta/Elev= 30
       0 2088.24    20.9 2080.54    34.6 2076.49    74.5 2066.78    82.4 2065.49
   100.3 2059.96   107.3 2059.82   118.2 2056.14   208.4 2037.85   221.8 2034.91
   235.2 2030.81   275.3 2030.73   311.3 2028.99   335.9 2030.07   343.12028.963
   350.3 2027.96   356.3 2028.94   359.3 2030.05   361.9 2030.09   376.3 2029.19
   383.3 2030.52   396.5 2031.49   444.7 2031.62   474.7 2033.69   504.6 2033.51
   517.8 2036.97   551.7  2053.3   564.5 2058.18   579.8 2061.21   596.9 2062.51
#Mann= 3 ,-1,0
       0      .1       0   343.1    .045       0   356.3      .1       0
Bank Sta=343.1,356.3
XS Rating Curve= 0 ,0
Exp/Cntr(USF)=0,0
Exp/Cntr=0.3,0.1

Type RM Length L Ch R = 1 ,7684    ,313.4,315.5,315.3
XS GIS Cut Line= 4
2279749.65859992 659244.349011852279689.29508394659144.276164714
2279643.62314124658926.4712542842279044.44097744658570.542146537
#Sta/Elev= 30
       0 2074.41    87.8 2051.71    97.1 2047.41   124.1 2030.63   132.3 2027.31
     165 2026.89   177.3 2024.53   246.7 2026.76   269.1 2025.75  280.64 2025.74
   287.6 2027.77   336.6 2027.87   413.2 2030.18   453.8 2029.09   478.3 2031.36
   515.6 2032.52   529.9  2031.7   547.2 2032.36   576.4 2030.14   585.4 2030.51
   600.4 2033.82   636.5 2033.61   794.7 2039.55   808.7 2039.27   841.2 2041.65
   934.3 2044.02   971.5 2046.08   990.8  2048.3    1018  2048.5  1036.3 2052.01
#Mann= 3 ,-1,0
       0      .1       0   269.1    .045       0  280.64      .1       0
Bank Sta=269.1,280.64
XS Rating Curve= 0 ,0
Exp/Cntr(USF)=0,0
Exp/Cntr=0.3,0.1

Type RM Length L Ch R = 1 ,7368    ,333.1,326.5,313.8
XS GIS Cut Line= 3
2279943.91717104659011.0232964932279882.89429065658725.634993363
 2279624.0540073658374.548673885
#Sta/Elev= 30
       0  2047.7    67.3 2031.95   112.3 2024.26   120.5 2019.86   128.7 2019.29
   136.9 2018.54  147.84 2019.29   153.2 2020.38   177.8 2021.05   263.7 2020.24
   356.8 2022.09   374.2 2021.23     440 2024.02   444.7 2023.56   451.4  2019.6
   456.4 2019.25   462.9 2020.34   471.3 2023.79   474.3 2024.16   482.9 2023.56
   548.7 2025.69   559.3 2024.72   575.7 2025.44   597.3  2031.1   625.4 2032.91
   630.3 2034.02   640.2 2041.55   694.1  2071.6   714.3 2082.02     728 2087.73
#Mann= 3 ,-1,0
       0      .1       0   128.7    .045       0  147.84      .1       0
#XS Ineff= 2 , 0
                          359.53         2031.51
Permanent Ineff=
       F       F
Bank Sta=128.7,147.84
XS Rating Curve= 0 ,0
Exp/Cntr(USF)=0,0
Exp/Cntr=0.3,0.1

Type RM Length L Ch R = 1 ,7042    ,228.1,234.5,234.7
XS GIS Cut Line= 3
2280300.33123212658743.5316779192280000.10351429658678.724813718
2279701.19838553658367.916383365
#Sta/Elev= 30
       0  2078.5    15.6 2072.42    24.7 2066.78    49.3 2055.36   122.9 2016.31
   139.3 2014.54   162.8 2015.47   183.9 2013.58   196.6 2015.22   262.1 2014.71
  273.38 2014.71   282.5 2016.53   322.3 2016.53   359.2 2018.16   375.9 2016.93
     387  2018.7   425.8 2018.51   468.6 2021.42   475.8 2021.42   486.9 2017.62
   497.7 2017.08   514.6 2021.75   586.8 2022.59   597.9 2023.24   620.1 2027.48
   644.8 2028.07   653.3 2031.87   673.1  2035.6   686.7 2039.81   738.4  2063.1
#Mann= 3 ,-1,0
       0      .1       0   262.1    .045       0  273.38      .1       0
#XS Ineff= 2 , 0
                          359.51         2020.09
Permanent Ineff=
       F       F
Bank Sta=262.1,273.38
XS Rating Curve= 0 ,0
Exp/Cntr(USF)=0,0
Exp/Cntr=0.3,0.1

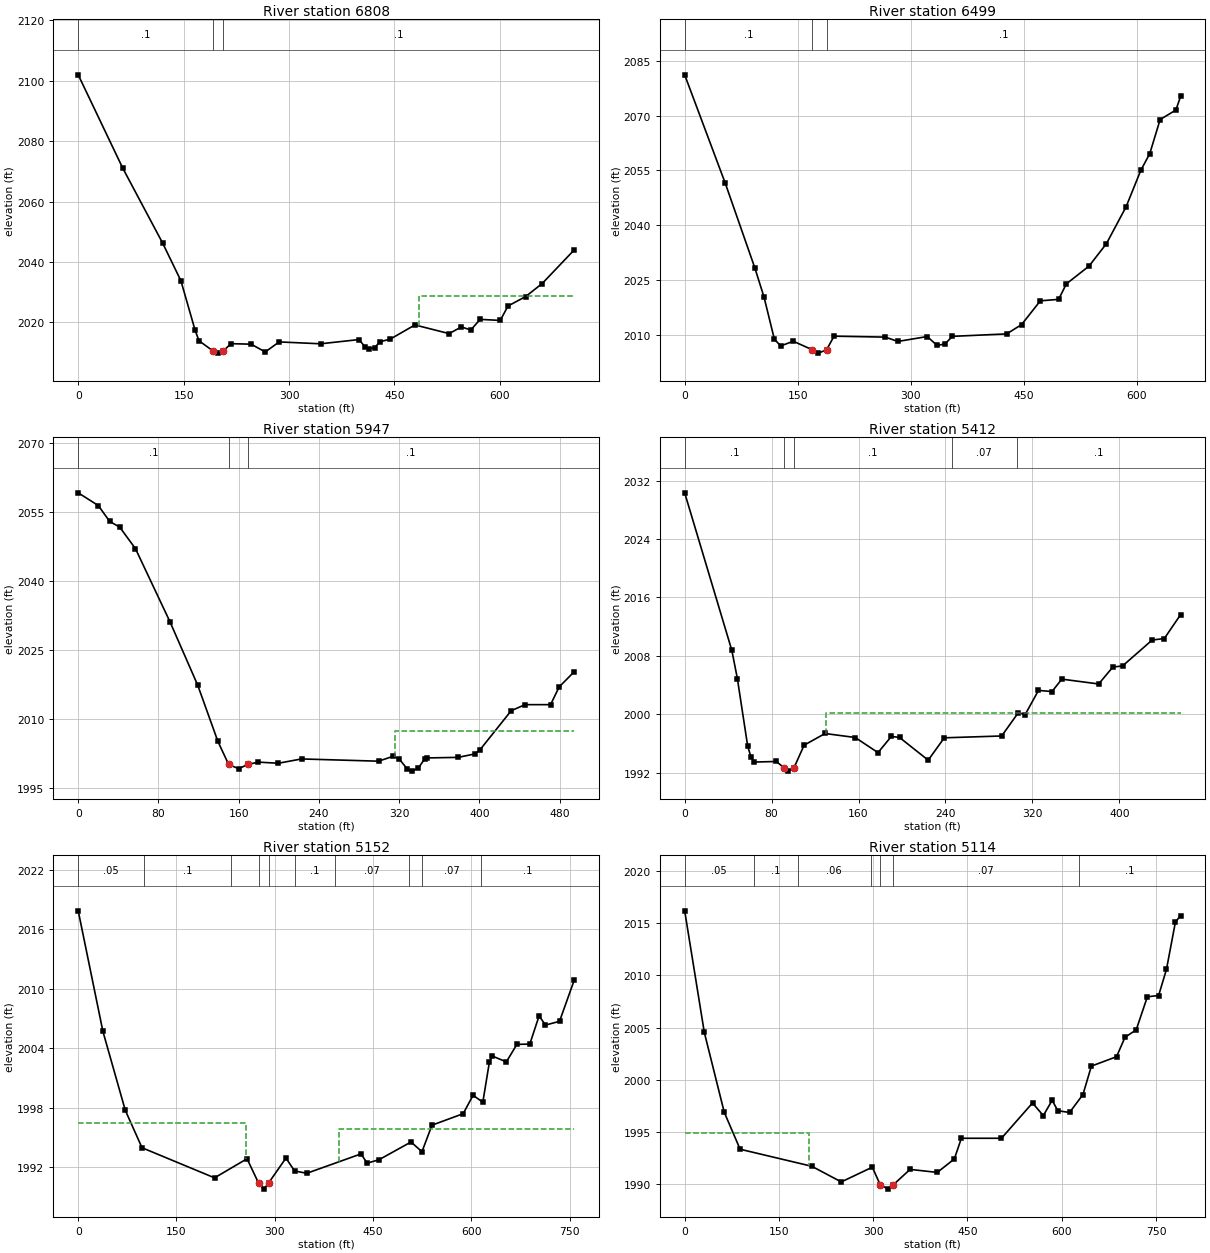
Type RM Length L Ch R = 1 ,6808    ,306.5,308.2,304.9
XS GIS Cut Line= 3
2280351.28251003658742.5859134552280163.58265112658490.437107875
2279997.45750501658136.008333866
#Sta/Elev= 30
       0 2101.93    63.3 2071.09   120.4 2046.13   146.2 2033.75   166.3 2017.43
   171.9 2013.92   191.9 2010.54   199.5 2009.83   206.2 2010.53   217.6 2012.96
   246.1 2012.79   266.2 2010.22     286 2013.54   344.9 2012.92   399.7 2014.32
   408.5  2011.8   414.1 2011.34   421.8 2011.57   429.1 2013.56   444.2 2014.48
   479.2 2019.16   527.8 2016.29   545.4  2018.5   558.7 2017.48     572    2021
   600.6 2020.65   611.7 2025.43   636.7 2028.54   660.3 2032.86   705.8 2043.97
#Mann= 3 ,-1,0
       0      .1       0   191.9    .045       0   206.2      .1       0
#XS Ineff= 2 , 0
                          484.79         2028.79
Permanent Ineff=
       F       F
Bank Sta=191.9,206.2
XS Rating Curve= 0 ,0
Exp/Cntr(USF)=0,0
Exp/Cntr=0.3,0.1

Type RM Length L Ch R = 1 ,6499    ,546,552.6,537.9
XS GIS Cut Line= 2
2280511.98630457658465.7555580452280038.12706999658008.790518036
#Sta/Elev= 30
       0 2081.16      54 2051.43      93 2028.41   105.3 2020.37   119.1 2008.79
   127.5    2007   144.2 2008.27   169.42005.937   177.6 2005.02  188.39 2005.95
   198.3 2009.66   266.2  2009.4   283.1 2008.22     322 2009.56     335 2007.12
   345.4 2007.52   355.4 2009.61   427.4 2010.28   447.2 2012.83   472.1 2019.33
   496.4 2019.73   506.6 2023.96   536.7 2028.83   559.8 2034.97   585.9 2045.05
   605.4    2055   617.4 2059.63   631.1 2068.93     652 2071.52   658.3 2075.27
#Mann= 3 ,-1,0
       0      .1       0   169.4    .045       0  188.39      .1       0
Bank Sta=169.4,188.39
XS Rating Curve= 0 ,0
Exp/Cntr(USF)=0,0
Exp/Cntr=0.3,0.1

Type RM Length L Ch R = 1 ,5947    ,529.7,534.3,526.1
XS GIS Cut Line= 2
 2280775.1518762658114.2192218442280381.19636163 657815.24924119
#Sta/Elev= 30
       0 2059.27      20 2056.51    31.4 2053.05    41.4 2051.81    57.1 2047.13
    91.4 2031.29   119.2 2017.44   139.3 2005.23  150.02 2000.22   159.9  1999.3
   169.4 2000.23   179.5 2000.73   199.6 2000.48   222.7 2001.42   299.5 2000.93
     314 2001.99   319.8 2001.48   328.3 1999.21   332.6 1998.77   339.2 1999.44
   345.5 2001.41   348.3 2001.64   378.9 2001.76   395.4  2002.5   400.4 2003.33
   431.8  2011.9   445.6 2013.22   471.1 2013.22   479.6 2017.06   494.6 2020.37
#Mann= 3 ,-1,0
       0      .1       0  150.02    .045       0   169.4      .1       0
#XS Ineff= 2 , 0
                          316.28         2007.41
Permanent Ineff=
       F       F
Bank Sta=150.02,169.4
XS Rating Curve= 0 ,0
Exp/Cntr(USF)=0,0
Exp/Cntr=0.3,0.1

Type RM Length L Ch R = 1 ,5412    ,270.4,260.6,249.5
XS GIS Cut Line= 3
2280918.14144307657812.7616433812280812.08241542657728.290057905
2280514.25346865657608.995087027
#Sta/Elev= 30
       0 2030.32    43.4 2008.75    48.5 2004.89      58 1995.63    60.9 1994.23
    63.7 1993.47    84.3 1993.55    91.3 1992.71      95 1992.23   100.7 1992.72
   109.9 1995.78   129.2 1997.38     157 1996.83   177.9 1994.76   190.2 1996.98
   197.7 1996.84   224.1 1993.73   238.9 1996.79   291.7 1997.04   307.1 2000.24
   313.3 1999.96   325.6 2003.28     338 2003.12   347.1 2004.82     381 2004.16
     394 2006.47     403 2006.63   430.2 2010.17   441.4 2010.38   456.4 2013.65
#Mann= 5 ,-1,0
       0      .1       0    91.3    .045       0   100.7      .1       0
  245.59     .07       0  305.59      .1       0
#XS Ineff= 2 , 0
                          130.02         2000.18
Permanent Ineff=
       F       F
Bank Sta=91.3,100.7
XS Rating Curve= 0 ,0
Exp/Cntr(USF)=0,0
Exp/Cntr=0.3,0.1

Type RM Length L Ch R = 1 ,5152    ,39.8,37.8,37.4
XS GIS Cut Line= 6
2281127.90322393657622.4689263612280969.47716896657494.138945096
2280838.77950533 657652.982546512280804.67279858657681.921570417
2280745.28785287657693.4361516852280528.17499516657586.561878028
#Sta/Elev= 30
       0 2017.87    37.7 2005.69    71.8 1997.73    97.4 1993.94   208.1  1990.9
   257.7 1992.83  275.45 1990.35   283.3 1989.76   290.5 1990.37   317.1  1992.9
   330.2  1991.6   348.9 1991.36   431.7 1993.32     441 1992.38   459.1 1992.73
     508 1994.52   524.7 1993.54     540 1996.22   587.6 1997.38   602.7 1999.24
   617.6 1998.54   627.7 2002.62   632.2  2003.2   653.5 2002.61   669.6 2004.38
   689.3 2004.41   703.5 2007.26   713.2 2006.33   734.7 2006.71     757 2010.85
#Mann= 10 ,-1,0
       0     .05       0     100      .1       0  233.88     .07       0
  275.45    .045       0   290.5     .07       0  331.51      .1       0
  391.51     .07       0  504.54      .1       0  525.03     .07       0
  615.03      .1       0
#XS Ineff= 2 , 0
          256.42 1996.48  398.53         1995.85
Permanent Ineff=
       F       F
Bank Sta=275.45,290.5
XS Rating Curve= 0 ,0
Exp/Cntr(USF)=0,0
Exp/Cntr=0.3,0.1

Type RM Length L Ch R = 1 ,5114    ,159.9,183.8,192.6
XS GIS Cut Line= 6
2281136.28325465657605.6489275342280954.08585861657455.614678338
2280823.38819499657614.4582797522280789.28148824 657643.39730366
2280729.89654252657654.9118849272280512.78368481657548.037611271
#Sta/Elev= 30
       0 2016.18    31.2 2004.55    62.9  1996.9    88.2 1993.35   202.2 1991.72
   249.2 1990.22   298.6 1991.63     3111989.966   323.6 1989.53  332.22 1989.96
   358.7 1991.42     402 1991.13   429.1 1992.42   440.3  1994.4   504.1  1994.4
   553.5 1997.78   570.7 1996.57   584.8 1998.04   593.7 1997.04   612.5 1996.87
   633.8 1998.59   647.2 2001.31   687.2 2002.21   700.7 2004.07   718.5 2004.78
   736.3 2007.95   754.2 2008.07   766.7 2010.58   780.9  2015.1   789.2 2015.73
#Mann= 7 ,-1,0
       0     .05       0     110      .1       0     180     .06       0
  296.02     .07       0     311    .045       0  332.22     .07       0
  627.17      .1       0
#XS Ineff= 2 , 0
          198.53 1994.89
Permanent Ineff=
       F       F
Bank Sta=311,332.22
XS Rating Curve= 0 ,0
Exp/Cntr(USF)=0,0
Exp/Cntr=0.3,0.1

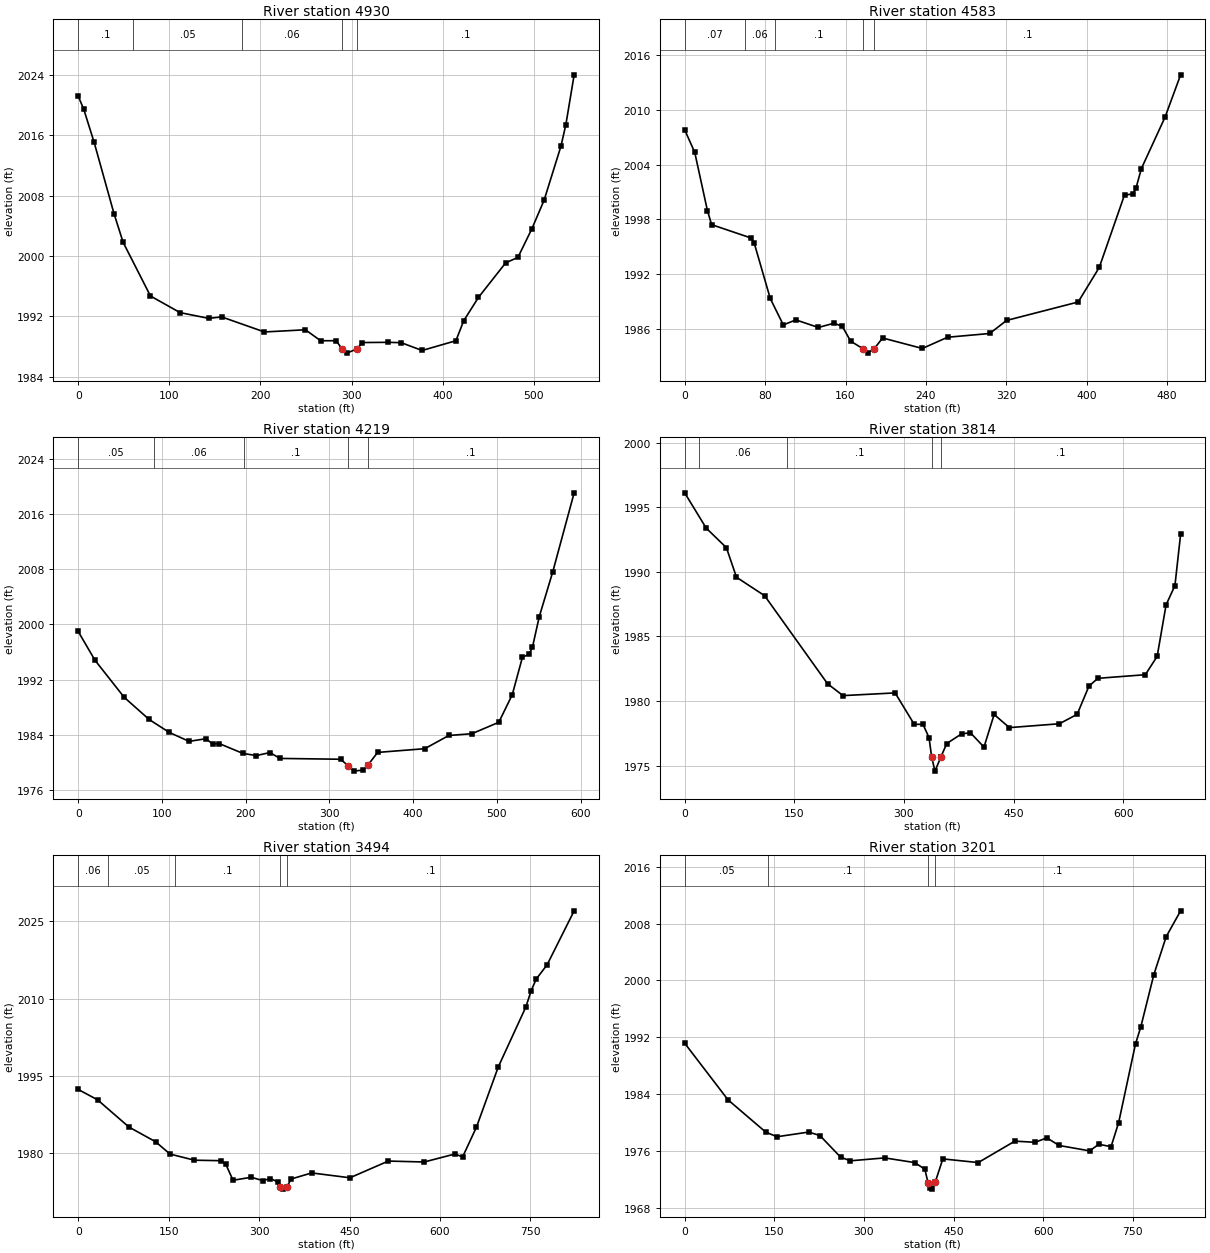
Type RM Length L Ch R = 1 ,4930    ,345.2,347.6,343.8
XS GIS Cut Line= 3
2281191.65249656 657566.19735473  2280834.878781657298.604798577
2280752.48426594657244.683548718
#Sta/Elev= 30
       0 2021.15     6.1 2019.41    17.5 2015.03    39.3  2005.6    49.3 2001.81
    79.3 1994.71   111.8 1992.51   143.2 1991.75   157.5 1991.94   204.4 1989.95
   249.4 1990.24   266.1 1988.79   283.2 1988.79   289.51987.729     295 1987.15
  306.28 1987.73   311.8 1988.55   340.4 1988.58   354.6 1988.53   377.5  1987.5
   414.6 1988.79   423.2 1991.44   439.4 1994.53   469.2 1999.09   482.7 1999.82
   498.1 2003.63   511.4 2007.38   529.9 2014.53   535.3 2017.38   544.4 2023.97
#Mann= 5 ,-1,0
       0      .1       0      60     .05       0     180     .06       0
   289.5    .045       0  306.28      .1       0
Bank Sta=289.5,306.28
XS Rating Curve= 0 ,0
Exp/Cntr(USF)=0,0
Exp/Cntr=0.3,0.1

Type RM Length L Ch R = 1 ,4583    ,361.4,363.3,351.6
XS GIS Cut Line= 2
2281325.75483211657214.258574536 2280854.9683895657066.937646916
#Sta/Elev= 30
       0 2007.82      10 2005.35    22.6 1998.98    26.8 1997.43      66 1995.97
    69.2  1995.4    85.1 1989.35    98.1 1986.45   110.6    1987     133 1986.17
   148.3 1986.63   156.7 1986.31   165.1 1984.67   177.7 1983.82   177.7 1983.81
   181.9 1983.36  188.321983.815   196.9 1985.02   236.4 1983.87   261.5  1985.1
   303.4 1985.51   320.2 1986.94   391.4 1988.96   412.4 1992.75   437.5 2000.69
   445.9 2000.78     449 2001.47   454.3 2003.58   477.8  2009.2   493.3 2013.84
#Mann= 5 ,-1,0
       0     .07       0      60     .06       0      90      .1       0
   177.7    .045       0  188.32      .1       0
Bank Sta=177.7,188.32
XS Rating Curve= 0 ,0
Exp/Cntr(USF)=0,0
Exp/Cntr=0.3,0.1

Type RM Length L Ch R = 1 ,4219    ,401.3,405.2,397.5
XS GIS Cut Line= 3
2281496.80309508657005.2795667122281426.76160189656910.593844428
2280954.63005515656862.602450941
#Sta/Elev= 30
       0 1998.97      20 1994.81    54.9 1989.44    84.7 1986.23   108.7 1984.36
   132.4 1983.06   152.5 1983.44   160.6 1982.68   168.6 1982.73   196.8 1981.31
   212.9    1981   228.9 1981.44     241 1980.59   313.4 1980.47   322.2 1979.54
   329.4 1978.75   340.4 1978.91   345.71979.579   357.6 1981.46   413.9    1982
   442.6 1983.91   470.2 1984.17   502.3 1985.82   518.4 1989.82   530.5 1995.23
   538.5 1995.69   542.5 1996.69   550.6  2001.1   566.7 2007.59   592.3 2019.05
#Mann= 5 ,-1,0
       0     .05       0      90     .06       0  197.78      .1       0
   322.2    .045       0   345.7      .1       0
Bank Sta=322.2,345.7
XS Rating Curve= 0 ,0
Exp/Cntr(USF)=0,0
Exp/Cntr=0.3,0.1

Type RM Length L Ch R = 1 ,3814    ,314.4,320.3,315.1
XS GIS Cut Line= 3
2281657.62666183656730.4032692612281481.48207446656628.986688653
2281012.49179066 656707.27317193
#Sta/Elev= 30
       0 1996.13    29.4  1993.4    57.1 1991.88    70.9 1989.59   109.4 1988.16
   195.5 1981.34   216.7 1980.42     288 1980.63   314.1  1978.2   326.2 1978.19
   334.4 1977.16  337.981975.668   342.5 1974.57   350.6 1975.66   350.6 1975.67
   358.7 1976.71     379 1977.46   391.1 1977.54   409.6 1976.43   423.5 1978.96
   444.3 1977.94   512.8 1978.24   537.1 1978.97   553.3 1981.16   565.5 1981.76
   630.4 1982.04   646.6 1983.46   658.8 1987.45   670.9 1988.94   678.7 1992.92
#Mann= 5 ,-1,0
       0     .05       0      20     .06       0     140      .1       0
  337.98    .045       0   350.6      .1       0
Bank Sta=337.98,350.6
XS Rating Curve= 0 ,0
Exp/Cntr(USF)=0,0
Exp/Cntr=0.3,0.1

Type RM Length L Ch R = 1 ,3494    ,280,293.1,285.4
XS GIS Cut Line= 4
2281604.09512964656413.8379229682281319.75281075 656390.49379259
2280985.22618743656510.397074761 2280864.9857449656646.751237904
#Sta/Elev= 30
       0 1992.41      32 1990.41    84.2 1985.12   128.4 1982.27   152.2 1979.89
   192.6  1978.7   236.7  1978.6   244.7 1977.92   256.8 1974.81   287.1 1975.39
   306.1 1974.74   318.8 1975.13   330.9  1974.5  335.34 1973.54   340.1 1973.09
   346.4 1973.54   352.8 1975.04   387.2 1976.23   450.6 1975.29   514.3 1978.53
   573.8 1978.35   624.8  1979.9   637.5 1979.33   660.4 1985.09   696.7 1996.79
   742.6 2008.45     751 2011.51   759.6 2013.81   777.7 2016.59   822.5 2027.04
#Mann= 5 ,-1,0
       0     .06       0      50     .05       0     160      .1       0
  335.34    .045       0   346.4      .1       0
Bank Sta=335.34,346.4
XS Rating Curve= 0 ,0
Exp/Cntr(USF)=0,0
Exp/Cntr=0.3,0.1

Type RM Length L Ch R = 1 ,3201    ,406.7,418.4,424.6
XS GIS Cut Line= 4
2281579.01306744 656364.118170492281232.10713725656287.551526425
2281058.64437533656349.0356154732280877.38882458656576.132955246
#Sta/Elev= 30
       0 1991.16    72.5 1983.18   135.7 1978.63   154.5 1977.98   207.7 1978.64
   226.3 1978.15     261  1975.1   277.4 1974.59   334.7    1975   384.9 1974.34
   401.9 1973.41  407.12 1971.53   410.4 1970.71   414.6  1970.6   419.1 1971.54
     432 1974.86   491.2 1974.34   552.5 1977.36   586.7  1977.2     606 1977.83
   626.5 1976.75   677.7 1975.99     693 1976.92   713.5 1976.58   726.2 1979.97
   754.4 1991.06   763.2 1993.43   785.1 2000.82   805.8 2006.18   829.9 2009.81
#Mann= 4 ,-1,0
       0     .05       0     140      .1       0  407.12    .045       0
   419.1      .1       0
Bank Sta=407.12,419.1
XS Rating Curve= 0 ,0
Exp/Cntr(USF)=0,0
Exp/Cntr=0.3,0.1

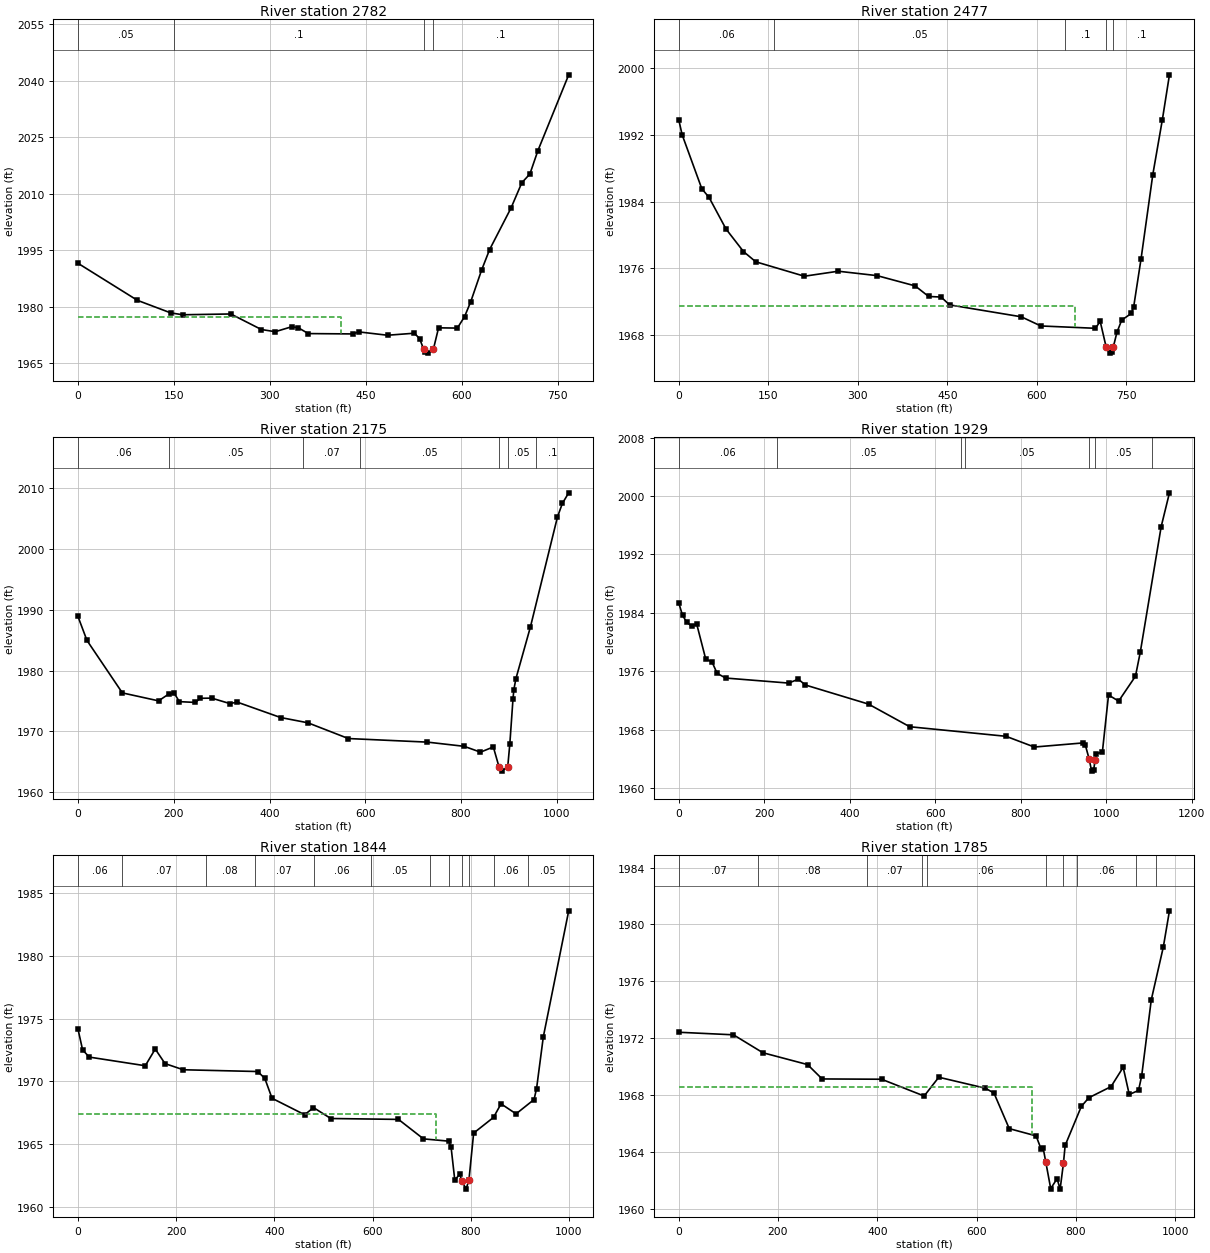
Type RM Length L Ch R = 1 ,2782    ,306.7,304.9,303.6
XS GIS Cut Line= 4
2281585.14580891656356.6984375652281339.04684823656283.175762226
2281220.40502124656182.5546515622280882.33383009656074.223269686
#Sta/Elev= 30
       0 1991.49    92.9 1981.65     145 1978.31   163.8 1977.81     239 1978.02
   286.8 1973.89   308.5 1973.31   334.1 1974.62   344.5 1974.36   360.3 1972.81
   429.5 1972.72   439.1 1973.26   484.1 1972.37   526.1 1972.91   534.3 1971.46
   540.5 1968.69   542.9 1967.91     548 1967.62  555.86  1968.7   563.9 1974.34
   593.3 1974.27   604.6 1977.32   614.3 1981.32   631.1 1989.64   643.7 1995.12
   677.3  2006.2   694.1 2012.88   706.7  2015.2   719.3 2021.43   767.4 2041.54
#Mann= 4 ,-1,0
       0     .05       0     150      .1       0   540.5    .045       0
  555.86      .1       0
#XS Ineff= 2 , 0
          410.69 1977.27
Permanent Ineff=
       F       F
Bank Sta=540.5,555.86
XS Rating Curve= 0 ,0
Exp/Cntr(USF)=0,0
Exp/Cntr=0.3,0.1

Type RM Length L Ch R = 1 ,2477    ,298.9,302,305.9
XS GIS Cut Line= 3
2281755.62225537656185.7587221632281439.38054255 655870.73163143
2281064.35170314655850.182882531
#Sta/Elev= 30
       0 1993.84     5.7 1992.03    38.7 1985.54    50.9 1984.49    79.2 1980.71
   108.5    1978   129.1 1976.77   210.5 1975.04   267.2 1975.64   332.3 1975.11
     396 1973.88   418.6 1972.61   439.6 1972.54   453.6  1971.6   573.8 1970.17
   606.6 1969.07     698 1968.79     706 1969.62  715.811966.591     722 1965.81
     726 1965.97   728.1 1966.58     734  1968.3     742 1969.77     758 1970.57
   762.1 1971.38   774.5 1977.16   794.1 1987.23   810.1 1993.82     822 1999.21
#Mann= 5 ,-1,0
       0     .06       0     160     .05       0  646.38      .1       0
  715.81    .045       0   728.1      .1       0
#XS Ineff= 2 , 0
          664.39 1971.46
Permanent Ineff=
       F       F
Bank Sta=715.81,728.1
XS Rating Curve= 0 ,0
Exp/Cntr(USF)=0,0
Exp/Cntr=0.3,0.1

Type RM Length L Ch R = 1 ,2175    ,243.1,246.6,248.2
XS GIS Cut Line= 4
2281779.86147476656136.036355887 2281194.8797772 655596.53026733
2281081.46249555655552.2244935692280997.91948567655619.454371342
#Sta/Elev= 30
       0 1988.92    18.8 1984.98    92.7 1976.35   168.3 1975.04     190 1976.18
   200.9 1976.31   211.8 1974.91   245.2 1974.78   255.3 1975.46   279.2 1975.49
   316.9  1974.6     333 1974.82   423.1  1972.3   480.2 1971.43   564.7 1968.84
   729.9 1968.25   806.6 1967.56   840.6  1966.6   867.4 1967.46   879.2  1964.2
   884.6 1963.48   897.5 1964.21   901.8  1967.9   908.5 1975.38   910.3  1976.9
   914.6  1978.7   944.9 1987.21  1001.3 2005.28  1011.6 2007.52  1024.8 2009.26
#Mann= 7 ,-1,0
       0     .06       0     190     .05       0     470     .07       0
     590     .05       0   879.2    .045       0   897.5     .05       0
  957.55      .1       0
Bank Sta=879.2,897.5
XS Rating Curve= 0 ,0
Exp/Cntr(USF)=0,0
Exp/Cntr=0.3,0.1

Type RM Length L Ch R = 1 ,1929    ,85.3,85.1,84.5
XS GIS Cut Line= 4
2281796.85191727656107.7764207142281161.36270934655412.745498771
2281117.00798518655350.6326132822281012.16905794655274.139424197
#Sta/Elev= 30
       0 1985.38     8.9 1983.66    18.8 1982.72    30.6 1982.15      42 1982.49
    63.1 1977.69    78.1 1977.25    89.9 1975.71   109.9 1975.07   257.1 1974.38
   279.8 1974.91   296.2 1974.12     444  1971.5   540.4  1968.4   765.7 1967.09
   831.9 1965.62   945.2 1966.18   951.1 1965.89   960.31963.934   965.8 1962.32
   970.7 1962.52   974.11963.873   976.7  1964.7     991 1964.94  1005.4 1972.75
    1029 1971.91  1068.4 1975.32  1079.8 1978.66  1128.5  1995.8  1147.9 2000.44
#Mann= 7 ,-1,0
       0     .06       0     230     .05       0     660     .06       0
     670     .05       0   960.3    .045       0   974.1     .05       0
 1108.09      .1       0
Bank Sta=960.3,974.1
XS Rating Curve= 0 ,0
Exp/Cntr(USF)=0,0
Exp/Cntr=0.3,0.1

Type RM Length L Ch R = 1 ,1844    ,59,58.3,59.2
XS GIS Cut Line= 4
2281826.65644939655870.7429690482281346.17833919655517.417159923
2281138.48663048655254.3357598152281072.25942872655239.113388067
#Sta/Elev= 30
       0 1974.18     9.4 1972.52    22.9 1971.94   137.1 1971.25   157.4 1972.58
   177.4 1971.42   214.6 1970.93   366.3 1970.79   380.6 1970.24   395.3 1968.66
   461.8 1967.35   479.7 1967.92     515 1967.05   652.8 1966.98   703.7 1965.43
   754.7 1965.25   759.8 1964.82   767.5 1962.15   777.4 1962.61   782.21962.083
   790.4 1961.43   796.3 1962.14   805.9 1965.89   846.4 1967.14   861.7 1968.22
   892.3 1967.42   928.9 1968.56     934 1969.42   947.8 1973.55   999.5 1983.58
#Mann= 12 ,-1,0
       0     .06       0      90     .07       0     260     .08       0
     360     .07       0     480     .06       0   596.4     .05       0
   716.4     .06       0   756.4     .05       0   782.2    .045       0
   796.3     .05       0   846.4     .06       0   916.4     .05       0
#XS Ineff= 2 , 0
           728.8 1967.37
Permanent Ineff=
       F       F
Bank Sta=782.2,796.3
XS Rating Curve= 0 ,0
Exp/Cntr(USF)=0,0
Exp/Cntr=0.3,0.1

Type RM Length L Ch R = 1 ,1785    ,165.1,155.9,140.1
XS GIS Cut Line= 4
2281850.03840165655809.4338362582281392.94350205655481.952628307
2281199.81075759655240.447469862 2281083.8731363655224.883922048
#Sta/Elev= 30
       0 1972.43   110.3 1972.25   169.6 1970.99   259.5 1970.16   288.9 1969.15
   408.6 1969.13   494.4 1967.95   523.9 1969.27   617.5  1968.5     635 1968.16
   665.8 1965.66   719.9 1965.15     730 1964.22   734.1  1964.3   739.2 1963.35
   749.3 1961.45   762.1 1962.14   768.3 1961.41     775 1963.24   778.4 1964.48
     811 1967.22   826.1 1967.83   870.8 1968.61   895.3 1969.97   907.5 1968.06
   926.2 1968.34   932.6 1969.38   951.9 1974.71   976.1 1978.41   988.5 1980.96
#Mann= 10 ,-1,0
       0     .07       0     160     .08       0     380     .07       0
     490     .08       0     500     .06       0   739.2    .045       0
     775     .07       0   802.3     .06       0  921.53     .05       0
  961.53     .06       0
#XS Ineff= 2 , 0
          711.55 1968.56
Permanent Ineff=
       F       F
Bank Sta=739.2,775
XS Rating Curve= 0 ,0
Exp/Cntr(USF)=0,0
Exp/Cntr=0.3,0.1

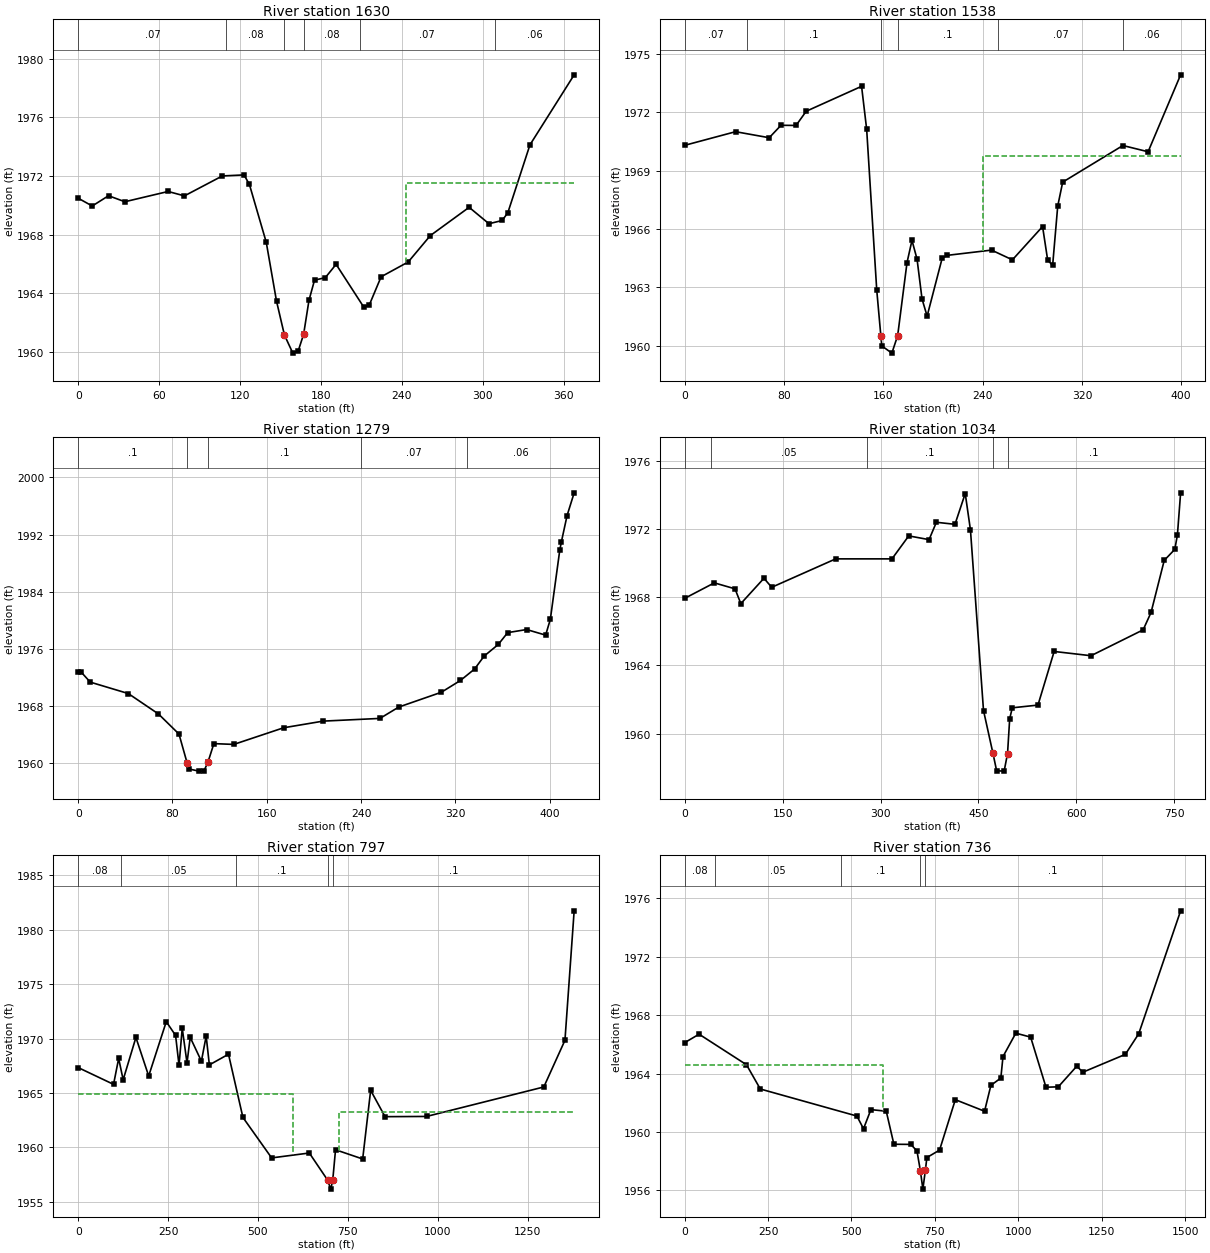
Type RM Length L Ch R = 1 ,1630    ,90,91.1,91.2
XS GIS Cut Line= 3
2281454.55262133655195.6403110872281266.57283432655176.634973629
2281092.21915418655217.166068828
#Sta/Elev= 30
       0 1970.48    10.4 1969.95    22.5 1970.65    34.6 1970.24    66.7 1970.94
    78.8 1970.64   106.9    1972     123 1972.07     127 1971.42   139.5 1967.47
   147.1 1963.46  152.951961.152   159.2 1959.91   163.2 1960.06   167.2 1961.19
   171.2 1963.52   175.3 1964.89   183.3 1965.06   191.3 1965.97   211.9 1963.04
     216 1963.21   224.7 1965.12   244.8 1966.13   261.2 1967.93     290 1969.86
   304.7 1968.74   314.5 1968.96   318.7 1969.49   335.1 1974.12   367.9  1978.9
#Mann= 6 ,-1,0
       0     .07       0     110     .08       0  152.95    .045       0
   167.2     .08       0  208.94     .07       0  308.94     .06       0
#XS Ineff= 2 , 0
                          243.53         1971.55
Permanent Ineff=
       F       F
Bank Sta=152.95,167.2
XS Rating Curve= 0 ,0
Exp/Cntr(USF)=0,0
Exp/Cntr=0.3,0.1

Type RM Length L Ch R = 1 ,1538    ,257.3,259,260
XS GIS Cut Line= 3
2281492.58603311655127.4832680992281312.54389375655096.152957518
2281098.22131127 655128.69759357
#Sta/Elev= 30
       0  1970.3      41    1971    68.1 1970.69    77.6 1971.33    89.7 1971.32
    97.9 1972.05   142.5 1973.33   146.6 1971.12   154.7 1962.88     158 1960.53
   158.8    1960   166.9 1959.63  171.57 1960.53   179.1 1964.28   183.1 1965.42
   187.2 1964.45   191.2 1962.41   195.3 1961.53   207.4  1964.5   211.4 1964.65
   247.2 1964.92     264 1964.42   288.3 1966.13   292.4 1964.41   296.4 1964.13
   300.5 1967.18   304.5 1968.41     353 1970.29   373.3 1969.97   399.5 1973.92
#Mann= 6 ,-1,0
       0     .07       0      50      .1       0     158    .045       0
  171.57      .1       0  252.75     .07       0  352.75     .06       0
#XS Ineff= 2 , 0
                          240.14         1969.76
Permanent Ineff=
       F       F
Bank Sta=158,171.57
XS Rating Curve= 0 ,0
Exp/Cntr(USF)=0,0
Exp/Cntr=0.3,0.1

Type RM Length L Ch R = 1 ,1279    ,246.6,245.1,241.3
XS GIS Cut Line= 4
2281406.48541101654931.3009655072281396.35913669654855.136086381
2281279.81001846654815.0110367572281060.07555794654835.565178987
#Sta/Elev= 30
       0 1972.72     2.1 1972.83    10.2 1971.35    42.5 1969.75    68.1 1966.89
    85.5 1964.08   92.351960.062    94.3 1959.18   102.4 1958.89   106.6  1958.9
     110  1960.1   115.1 1962.74     132 1962.63   174.3 1964.96   207.8 1965.89
     256 1966.27     272 1967.86   308.1 1969.93   324.3 1971.58   336.3 1973.18
   344.4 1974.99   356.4 1976.62   364.4 1978.28   380.5 1978.71   396.6 1977.93
   400.6 1980.15   408.6 1989.83     410 1991.01   414.8 1994.67   420.8 1997.85
#Mann= 5 ,-1,0
       0      .1       0   92.35    .045       0     110      .1       0
   240.1     .07       0   330.1     .06       0
Bank Sta=92.35,110
XS Rating Curve= 0 ,0
Exp/Cntr(USF)=0,0
Exp/Cntr=0.3,0.1

Type RM Length L Ch R = 1 ,1034    ,224.3,237.3,242.4
XS GIS Cut Line= 4
2281672.38319732654969.2716084852281482.50190502654613.443640568
2281190.49958157654597.487229451 2281127.3273681 654606.72584788
#Sta/Elev= 30
       0 1967.94    45.4 1968.85    77.1  1968.5      86 1967.63   121.4 1969.12
   133.3 1968.59   231.3 1970.26   317.5 1970.26   343.2 1971.61   374.3 1971.39
   385.5 1972.41     414 1972.29   429.7  1974.1   437.7 1971.96   457.7 1961.35
  472.211958.827   477.8 1957.81   489.3 1957.79   494.5 1958.82   497.8 1960.87
   501.8 1961.51   541.1 1961.67   565.9 1964.82   622.3 1964.57   702.2 1966.09
   714.3 1967.11   734.5 1970.17   750.7 1970.82   754.7 1971.67   759.6 1974.14
#Mann= 5 ,-1,0
       0      .1       0      40     .05       0     280      .1       0
  472.21    .045       0   494.5      .1       0
Bank Sta=472.21,494.5
XS Rating Curve= 0 ,0
Exp/Cntr(USF)=0,0
Exp/Cntr=0.3,0.1

Type RM Length L Ch R = 1 ,797     ,59.1,60.5,59.8
XS GIS Cut Line= 3
2281797.86200495655033.7248661852281264.73389196653929.070397911
2281129.51178449653857.900867659
#Sta/Elev= 30
       0 1967.34    98.3  1965.8   112.5 1968.18     125 1966.22   160.5 1970.11
     196 1966.57   244.9 1971.56   270.8  1970.3   280.4 1967.55   289.3 1970.96
   302.6 1967.77   311.5 1970.12   342.6 1967.93   355.9 1970.23   364.8 1967.59
     418 1968.57   458.1 1962.76     538 1959.04   642.8 1959.49   693.7    1957
   702.4 1956.17  707.931956.989   715.7 1959.79   791.2 1958.94   813.4 1965.25
   853.4 1962.83   968.8 1962.85    1295 1965.56  1353.8 1969.85  1379.4 1981.75
#Mann= 5 ,-1,0
       0     .08       0     120     .05       0     440      .1       0
   693.7    .045       0  707.93      .1       0
#XS Ineff= 2 , 0
          596.72 1964.87  724.93         1963.22
Permanent Ineff=
       F       F
Bank Sta=693.7,707.93
XS Rating Curve= 0 ,0
Exp/Cntr(USF)=0,0
Exp/Cntr=0.3,0.1

Type RM Length L Ch R = 1 ,736     ,80.4,78.5,79.2
XS GIS Cut Line= 3
 2281846.6351812655008.0766248432281284.68340847653842.572208204
2281111.02975465653758.592162507
#Sta/Elev= 30
       0 1966.11    43.2 1966.69   185.3  1964.6   226.7 1962.94   516.3 1961.09
   536.1 1960.22   558.3 1961.53   604.3 1961.42   627.2 1959.16     678 1959.15
   696.4  1958.7  706.551957.355   714.1 1956.09  721.551957.368   726.1 1958.25
   764.1 1958.76   811.4 1962.21     899 1961.42     918 1963.19   947.8 1963.69
   954.3 1965.16   992.7 1966.76  1037.2 1966.49  1083.2 1963.06  1120.1 1963.09
  1175.5  1964.5  1193.8 1964.09  1321.1 1965.31  1361.2 1966.72  1486.8 1975.13
#Mann= 5 ,-1,0
       0     .08       0      90     .05       0     470      .1       0
  706.55    .045       0  721.55      .1       0
#XS Ineff= 2 , 0
          594.23 1964.61
Permanent Ineff=
       F       F
Bank Sta=706.55,721.55
XS Rating Curve= 0 ,0
Exp/Cntr(USF)=0,0
Exp/Cntr=0.3,0.1