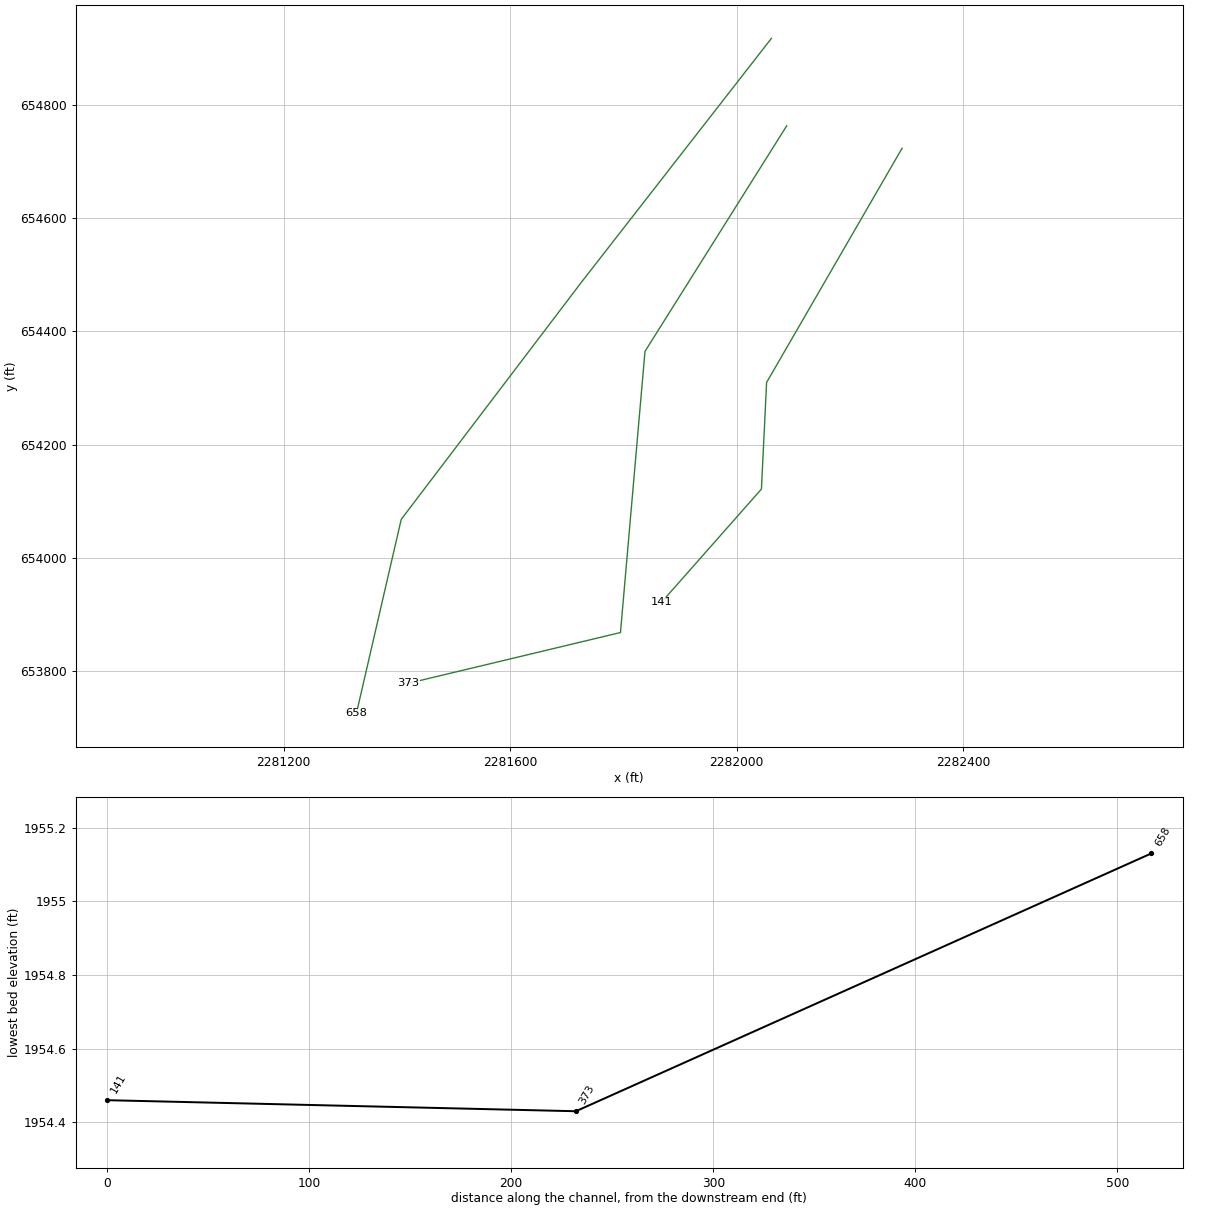
HEC-RAS study CSSTYRN.prj: CSSTYRN

--- CSSTYRN.g01 (geometry) --- (continued)

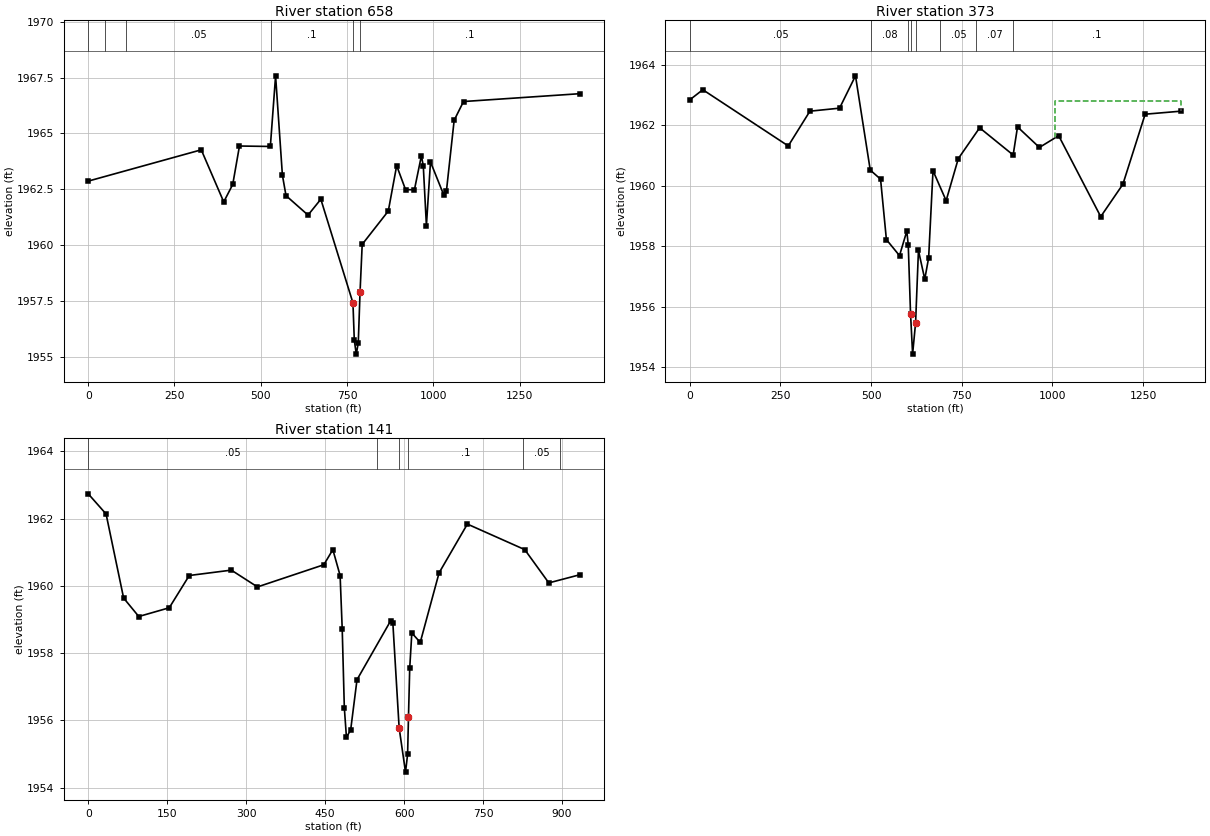
Type RM Length L Ch R = 1 ,658     ,279.3,284.8,286.2
XS GIS Cut Line= 4
2282061.52013676654917.5732291182281725.56825094654486.289103497
2281407.67265474654067.9695731872281328.52819492653725.297438186
#Sta/Elev= 30
       0 1962.87   327.6 1964.27   392.7 1961.94   418.8 1962.72   438.3 1964.44
   527.8 1964.42     543 1967.58   562.7 1963.14   573.2 1962.22     637 1961.35
   674.1 1962.06   767.2 1957.42   771.1 1955.75   776.8 1955.13   782.6 1955.63
  787.791957.919     794 1960.04   869.6 1961.53   893.9 1963.56   919.6 1962.49
   945.3 1962.48   965.5    1964     971 1963.56   980.1 1960.88   991.9 1963.73
  1030.9 1962.23  1038.2 1962.44  1060.5 1965.59  1087.6 1966.43  1423.8 1966.78
#Mann= 6 ,-1,0
       0     .05       0      50     .08       0     110     .05       0
     530      .1       0   767.2    .045       0  787.79      .1       0
Bank Sta=767.2,787.79
XS Rating Curve= 0 ,0
Exp/Cntr(USF)=0,0
Exp/Cntr=0.3,0.1

Type RM Length L Ch R = 1 ,373     ,229.8,232,229.5
XS GIS Cut Line= 4
2282088.56344398654763.150498222 2281838.2179197654364.664732518
2281794.90891767653868.0874837472281420.69633245653778.510869389
#Sta/Elev= 30
       0 1962.84    36.5 1963.18   271.9 1961.32   331.6 1962.47   413.3 1962.57
   457.2 1963.64   497.9 1960.52   526.3 1960.22   542.4 1958.22   578.5 1957.69
   598.6  1958.5   602.6 1958.05   608.91955.774   614.6 1954.43  622.841955.469
   630.7 1957.86   648.1 1956.91   658.8 1957.62   670.8  1960.5     707 1959.51
   740.5  1960.9   799.3 1961.92   891.7 1961.02   903.7 1961.95     964 1961.27
  1017.1 1961.66    1133 1958.98    1194 1960.05  1255.4 1962.37  1353.8 1962.47
#Mann= 8 ,-1,0
       0     .05       0   500.6     .08       0   600.6      .1       0
   608.9    .045       0  622.84      .1       0   690.6     .05       0
   790.6     .07       0   890.6      .1       0
#XS Ineff= 2 , 0
                         1006.67         1962.81
Permanent Ineff=
       F       F
Bank Sta=608.9,622.84
XS Rating Curve= 0 ,0
Exp/Cntr(USF)=0,0
Exp/Cntr=0.3,0.1

Type RM Length L Ch R = 1 ,141     ,,,
XS GIS Cut Line= 4
2282292.25852578654723.3772455972282053.00251787654309.788527661
2282043.87545789654121.4444844882281867.32740812653921.498500416
#Sta/Elev= 30
       0 1962.74    33.9 1962.14    67.2 1959.64      96 1959.09   153.9 1959.35
   191.9 1960.31   271.8 1960.47   321.4 1959.97   447.5 1960.63   464.6 1961.08
   478.4 1960.31   482.4 1958.72   486.4 1956.38   490.4  1955.5   498.4 1955.71
   510.5 1957.21   574.7 1958.97   578.6 1958.89   590.5 1955.78   602.6 1954.46
   606.6 1954.99  608.251956.097   610.6 1957.55   614.6  1958.6   630.6 1958.32
   666.4 1960.39   720.1 1961.84   829.1 1961.08   874.8 1960.09   933.1 1960.33
#Mann= 6 ,-1,0
       0     .05       0  547.81      .1       0   590.5    .045       0
  608.25      .1       0  826.37     .05       0  896.37      .1       0
Bank Sta=590.5,608.25
XS Rating Curve= 0 ,0
Exp/Cntr(USF)=0,0
Exp/Cntr=0.3,0.1
LCMann Table=0

Chan Stop Cuts=-1
Use User Specified Reach Order=0
Composite Channel Slope=5